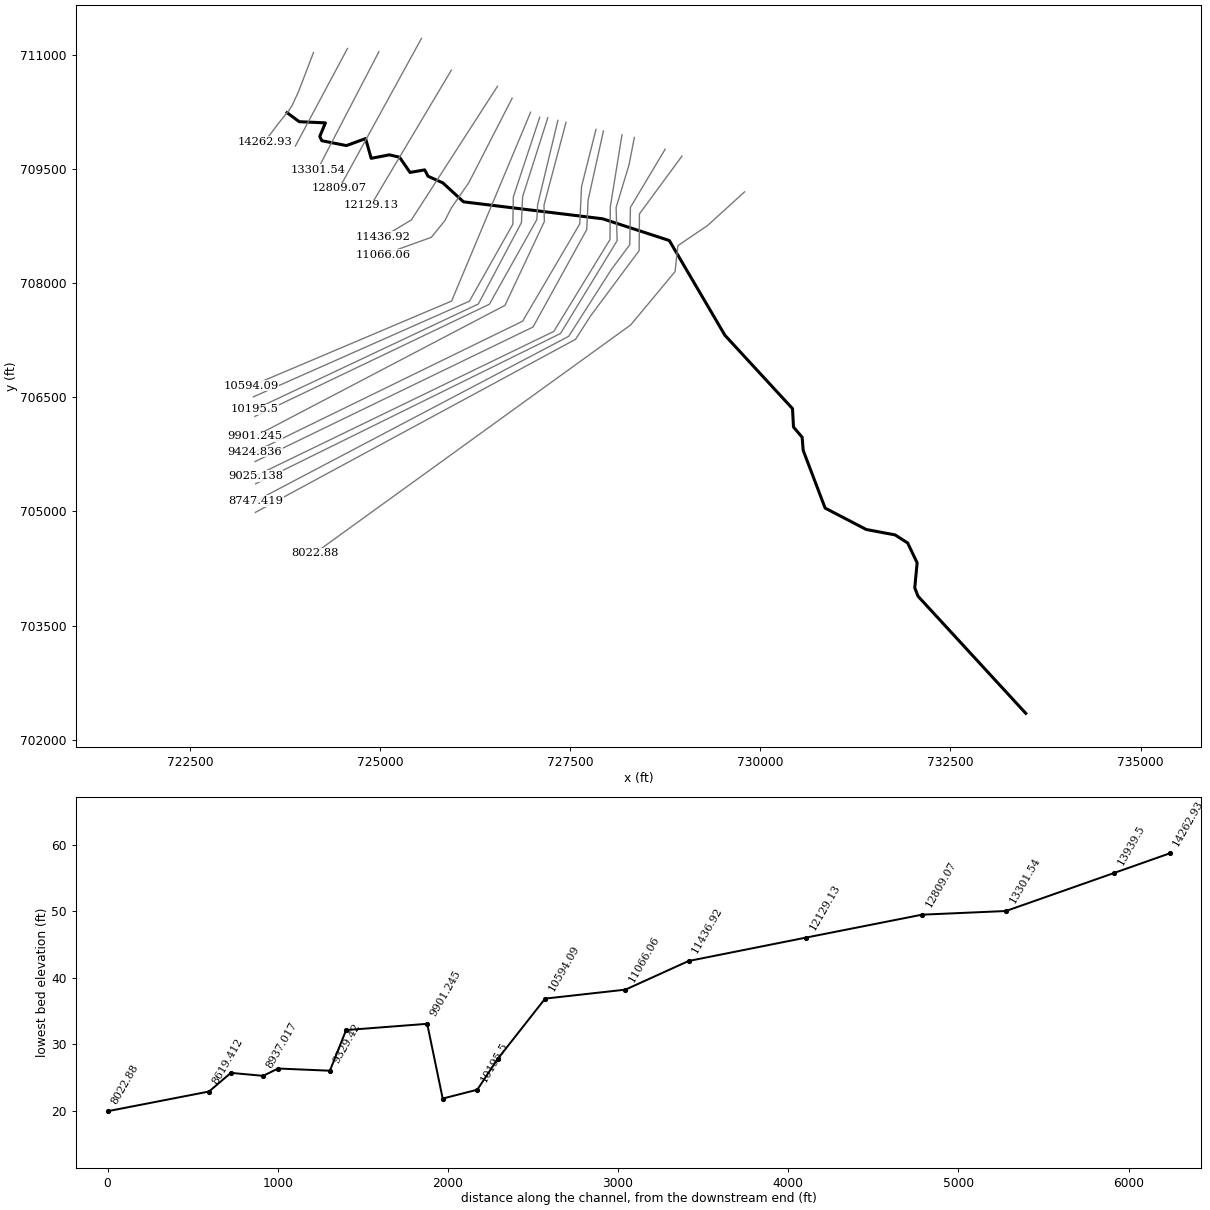
--- 6177_ras.prj (project) ---

Proj Title=6177
Current Plan=p01
Default Exp/Contr=0.3,0.1
English Units
Geom File=g01
Flow File=f01
Plan File=p01
Y Axis Title=Elevation
X Axis Title(PF)=Main Channel Distance
X Axis Title(XS)=Station
BEGIN DESCRIPTION:
RFD model 6177 exported to HEC-RAS
END DESCRIPTION:

--- 6177_ras.p01 (plan) ---

Plan Title=Plan 01
Program Version=4.10
Short Identifier=Plan 01
Geom File=g01
Flow File=f01
Subcritical Flow
Calc Critical at every XS
Secant Critical Depth

--- 6177_ras.f01 (steady flow) ---

Flow Title=Flow 01
Program Version=5.01
Number of Profiles= 6
Profile Names=10yr,25yr,50yr,100yr,100plus,500yr
River Rch & RM=6177,28,14262.93
 1650.94  3158.7 4801.99 6599.43 9635.1714481.68
River Rch & RM=6177,28, 13939.5
 1655.27 3167.59 4816.11 6619.58 9664.5914523.22
River Rch & RM=6177,28,13301.54
 1661.17 3179.68 4835.33    6647 9704.6214579.72
River Rch & RM=6177,28,12809.07
    1663 3183.45 4841.32 6655.55  9717.114597.36
River Rch & RM=6177,28,12129.13
 1675.99 3210.08 4883.61 6715.87 9805.1714721.48
River Rch & RM=6177,28,11436.92
 1686.53 3231.78 4918.14 6765.21 9877.2114823.28
River Rch & RM=6177,28,11066.06
 1688.25 3235.32 4923.78 6773.27 9888.9814839.92
River Rch & RM=6177,28,10594.09
 1783.86 3431.75 5236.13  7219.310540.1815754.08
River Rch & RM=6177,28,10314.52
 1784.49 3433.03 5238.18 7222.2310544.4615760.07
River Rch & RM=6177,28, 10195.5
 1787.59 3439.43 5248.38 7236.8310565.77   15790
River Rch & RM=6177,28,9992.255
    1790 3444.39 5256.28 7248.1210582.2515813.08
River Rch & RM=6177,28,9901.245
  1798.2 3461.33 5283.31 7286.8210638.7515892.46
River Rch & RM=6177,28,9424.836
 1802.31 3469.84 5296.89  7306.3 10667.215932.53
River Rch & RM=6177,28, 9329.42
 1802.83 3470.92 5298.63 7308.7810670.8315937.64
River Rch & RM=6177,28,9025.138
 1803.96 3473.26 5302.37 7314.1610678.6715948.71
River Rch & RM=6177,28,8937.017
 1804.22  3473.8 5303.24  7315.410680.4815951.26
River Rch & RM=6177,28,8747.419
 1805.18 3475.78  5306.4 7319.9510687.1215960.63
River Rch & RM=6177,28,8619.412
 1805.44 3476.32 5307.27 7321.1910688.9315963.18
River Rch & RM=6177,28, 8022.88
 1840.04    3548 5421.83  7485.510928.84 16300.6
River Rch & RM=6177,28,7759.896
 2200.43 4270.52 6554.69 9083.5513261.9819405.45
River Rch & RM=6177,28,7318.778
 2213.93 4298.61 6599.72 9148.3213356.5419535.37
River Rch & RM=6177,28,6409.238
  2418.5 4720.87 7273.8310114.2614766.8221441.09
River Rch & RM=6177,28,5314.048
 2429.59 4744.03 7311.0910167.9914845.2721547.88
River Rch & RM=6177,28,4094.801
 2437.68 4760.98  7338.410207.4414902.8721626.51
River Rch & RM=6177,28,2898.359
 3056.93 5979.19 9226.7912843.1618751.0226376.76
River Rch & RM=6177,28,1932.514
 3111.64 6094.04 9412.0613110.9719142.0126893.36
River Rch & RM=6177,28,       0
 3191.31 6262.49    968513506.9819720.1927661.04
Boundary for River Rch & Prof#=6177,28,1
Up Type= 0
Dn Type= 2
Boundary for River Rch & Prof#=6177,28,2
Up Type= 0
Dn Type= 2
Boundary for River Rch & Prof#=6177,28,2
Up Type= 0
Dn Type= 2
Boundary for River Rch & Prof#=6177,28,2
Up Type= 0
Dn Type= 2
Boundary for River Rch & Prof#=6177,28,2
Up Type= 0
Dn Type= 2
Boundary for River Rch & Prof#=6177,28,2
Up Type= 0
Dn Type= 2

--- 6177_ras.g01 (geometry) ---

Geom Title=6177
Program Version=4.10

River Reach=6177,28
Reach XY= 30
723776.946072668710243.798007756723936.841906041710125.048007756
724281.373156041710109.596618876724207.154406011709931.211202204
724234.498156041709874.787591085724557.414822698709810.985507771
724810.018989325709902.999396637724883.369683772709643.450785533
725123.387044877 709689.45772998725256.199544907709657.773702204
725393.786350489709458.120924428725586.928711593709491.541063324
725631.199544877709407.773702189725825.643989354709320.534118876
726097.236871272709071.510681376727927.097982377  708848.4204036
728802.966037959708562.830125824729534.736871302707316.302348033
730422.757704645706352.760681361730435.778537959706110.573181361
 730549.49381575705976.024570256730563.382704645705803.281514704
730851.691854268705045.083272055731392.469904989704763.365104049
   731772.060038704692.188234508731936.646593511704586.267625839
732061.646593511704325.850959137732030.198846042703995.950168937
732073.547101051703885.447435662733490.424320966702345.674143761

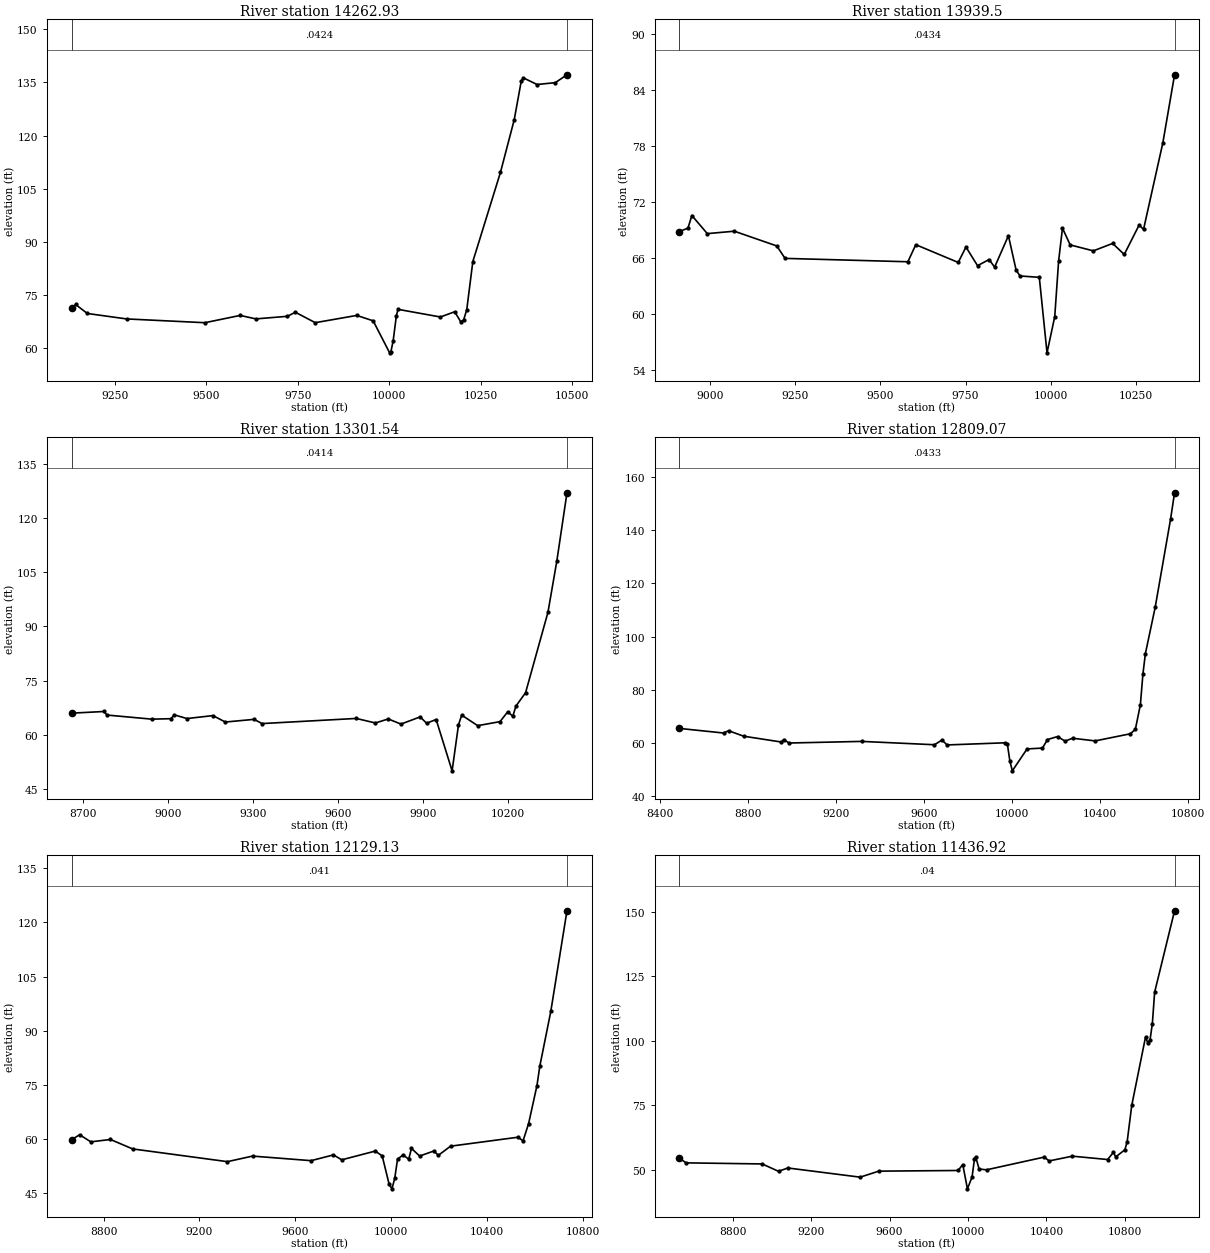
Type RM Length L Ch R = 1 ,14262.93,323.423100,323.423100,323.423100
XS GIS Cut Line= 6
724124.905997336711034.847918943723930.494008571 710527.04749696
723844.151964486710338.681346893723797.797991991710267.287544668
723672.383446336710113.904715136723480.258705616709859.413528129
#Sta/Elev= 30
9132.312 71.30169142.85772.368779174.98169.833879282.05968.299469496.21567.23255
9592.58669.288059635.41768.30717 9721.6969.036599743.396 70.18199797.76667.23909
9911.09969.285779955.95567.76746   1000158.7359710004.0958.8404810010.7362.18548
10019.4569.2215110023.9170.9998910139.7868.8454310178.8670.32249 10195.3 67.4885
10203.1367.9979610211.7570.9036310228.3384.4751410303.91109.655110341.42124.4413
10360.56135.313210366.37136.276410403.79 134.40110453.68 134.919 10485.6 137.143
#Mann= 3 , 0 , 0
9132.312  0.0424       09132.312  0.0424       0 10485.6  0.0424       0
#XS Ineff= 2 , 0
       0                10461.75       0
Bank Sta=9132.312,10485.6
Exp/Cntr=0.3,0.1

Type RM Length L Ch R = 1 , 13939.5,637.959800,637.959800,637.959800
XS GIS Cut Line= 2
724571.278140187 711087.44853273723885.994185835709804.630398721
#Sta/Elev= 30
8909.33168.806398934.78269.198568946.119 70.54268991.46968.599479070.83168.85759
9195.54367.276159219.77965.941779580.57265.57977 9603.6967.413169728.40265.50543
9751.07767.161389785.08965.160929819.10165.819069835.24965.001129875.78868.37516
9898.46364.67955  9909.864.056779966.48863.908629989.16255.8084110011.8459.69649
10023.1765.6479510034.5169.1874310057.1967.3876810125.2166.74955 10181.9 67.5468
10215.9166.3624310259.7169.52079 10272.669.0520910329.2978.3363310363.7285.64022
#Mann= 3 , 0 , 0
8909.331  0.0434       08909.331  0.0434       010363.72  0.0434       0
#XS Ineff= 2 , 0
       0                               0
Bank Sta=8909.331,10363.72
Exp/Cntr=0.3,0.1

Type RM Length L Ch R = 1 ,13301.54,492.474800,492.474800,492.474800
XS GIS Cut Line= 2
724984.955649197711045.662925765724178.493434668709495.416907117
#Sta/Elev= 30
8660.69666.018388774.16566.477818785.43765.491228943.248   64.369010.88164.48663
9022.15365.555899067.24264.525429158.97165.345039202.509 63.56199303.958 64.3004
9332.31863.136079664.669 64.55499732.30263.298589777.39164.411429822.47962.99646
9890.113 64.98659912.65763.238869946.47464.2588710002.8350.0588910025.3862.77943
10036.6565.4790210093.0162.5590610171.9263.6726510199.0566.3895410217.0165.17218
10228.2867.99627 10262.171.68121   1034193.90997 10372.4108.128810408.16126.9946
#Mann= 3 , 0 , 0
8660.696  0.0414       08660.696  0.0414       010408.16  0.0414       0
#XS Ineff= 2 , 0
       09062.176        10335.74       0
Bank Sta=8660.696,10408.16
Exp/Cntr=0.3,0.1

Type RM Length L Ch R = 1 ,12809.07,679.941700,679.941700,679.941700
XS GIS Cut Line= 2
725544.882782578711221.162475035724462.635562062709248.881825998
#Sta/Elev= 30
8488.435 65.46578689.37663.736058712.189 64.59978780.62962.537958951.72860.35102
8963.13461.258918987.08659.973699316.73960.58168 9647.5359.324939681.74961.10274
9704.56359.249829966.91460.052419978.32159.751879989.72753.3275410001.1349.50905
10068.0357.7528410138.0158.0679910160.8361.2809610206.4562.4024510240.67 60.6937
10274.8961.7698910377.5560.7713910537.2463.4447610560.0665.1281610582.8774.38391
10594.28 85.849710605.6893.6384310650.07110.997510719.75144.088410738.13154.1022
#Mann= 3 , 0 , 0
8488.435  0.0433       08488.435  0.0433       010738.13  0.0433       0
#XS Ineff= 2 , 0
       09342.879        10555.34       0
Bank Sta=8488.435,10738.13
Exp/Cntr=0.3,0.1

Type RM Length L Ch R = 1 ,12129.13,692.210000,692.210000,692.210000
XS GIS Cut Line= 2
725937.667488098710803.306405336724880.491631776709027.418109044
#Sta/Elev= 30
8667.01459.729298699.95661.077038746.507 59.11178828.62559.764748921.07457.14649
9316.75853.611349421.49755.15631 9665.8953.885819758.99255.485149793.90654.12248
9933.55956.546099962.50255.221419991.74847.3076710003.3946.0666710015.0249.01942
10026.6654.3050810049.9455.4927810073.2154.2875410084.8557.28468 10118.955.17272
10177.9556.55835 10197.155.3713310247.78 57.904710529.4460.3949610550.3659.36676
10573.6464.1868610608.55 74.738610620.1980.0528610666.2995.3303210733.75123.2408
#Mann= 3 , 0 , 0
8667.014   0.041       08667.014   0.041       010733.75   0.041       0
#XS Ineff= 2 , 0
       09607.902        10517.41       0
Bank Sta=8667.014,10733.75
Exp/Cntr=0.3,0.1

Type RM Length L Ch R = 1 ,11436.92,370.853500,370.853500,370.853500
XS GIS Cut Line= 3
726543.558789223 710590.19980976725412.297564268708834.425290242
725038.063293815708608.353525072
#Sta/Elev= 30
8528.034  54.476  8562.352.621098950.57852.19909 9033.8549.338539081.43350.63076
9450.207 47.06589545.37549.399869949.83749.656849973.629 51.97029997.42142.53047
10021.2147.1657810033.1153.9827810039.3555.03059 10056.950.2336410094.7449.91379
10389.9954.8722110413.78 53.363910532.7455.2145910712.2853.9165210742.0556.68829
10753.7354.9333110800.4657.6872510812.1560.8314510835.51  74.92310905.68101.4341
10917.2999.2518310928.98100.420710940.66 106.71710952.34118.908611053.91150.5108
#Mann= 3 , 0 , 0
8528.034    0.04       08528.034    0.04       011053.91    0.04       0
#XS Ineff= 2 , 0
       09903.393        10400.93       0
Bank Sta=8528.034,11053.91
Exp/Cntr=0.3,0.1

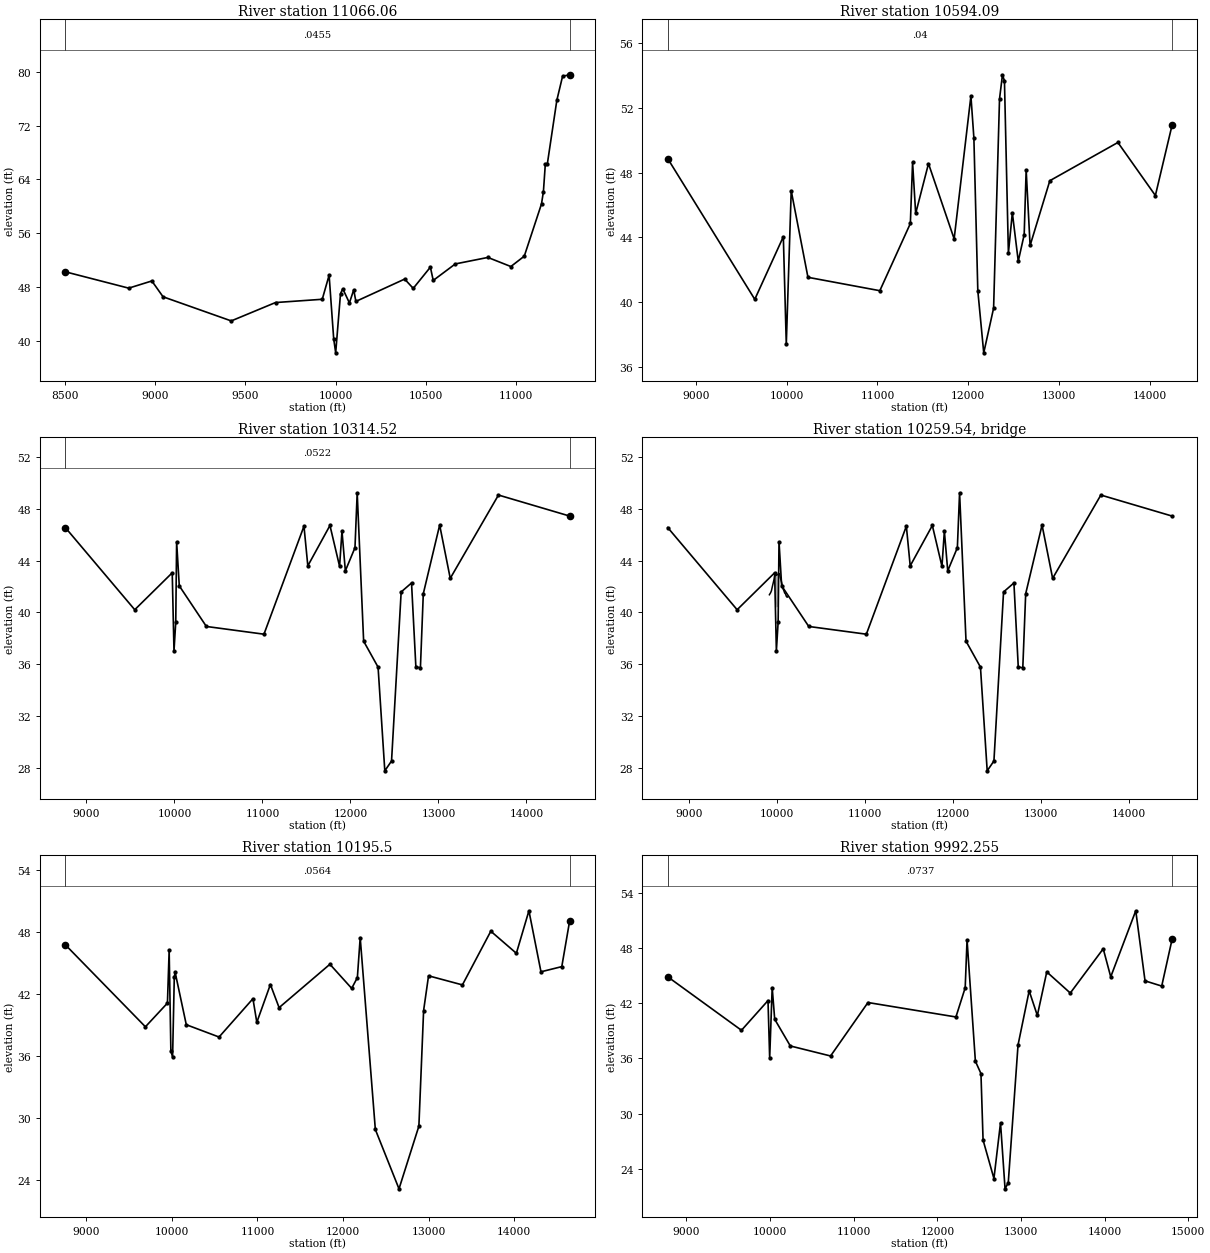
Type RM Length L Ch R = 1 ,11066.06,471.969900,471.969900,471.969900
XS GIS Cut Line= 6
726736.383401841710433.204093203726165.771485507709321.555780098
725939.745316893708995.493309781725850.622436285708822.409481302
725673.730960906708604.693526059725038.063293815 708375.95043014
#Sta/Elev= 30
8500.94450.263268852.70547.833568981.00148.902299043.24346.547969421.53342.96272
9667.09745.692569926.51846.178459964.52649.759539989.86540.33576   1000138.21696
10027.7847.0162610040.3847.73869 10077.245.6337210101.0947.5862510113.0345.86214
10383.6749.1807110431.2547.80074 10526.450.9530510542.2548.9811710664.7251.43433
10845.3952.3993310972.9251.0475911047.3252.5846511142.9760.36018 11153.662.19848
11164.2266.3046711174.8566.2221111227.9975.7548611259.8779.3377711299.1379.55265
#Mann= 3 , 0 , 0
8500.944  0.0455       08500.944  0.0455       011299.13  0.0455       0
#XS Ineff= 2 , 0
       09942.547        10220.43       0
Bank Sta=8500.944,11299.13
Exp/Cntr=0.3,0.1

Type RM Length L Ch R = 1 ,10594.09,279.572600,279.572600,279.572600
XS GIS Cut Line= 4
726979.463685632710249.301651537725940.787255943707766.864984423
 723494.95369342706731.196427882723306.103709936706651.229420811
#Sta/Elev= 30
8691.27548.868249649.86340.173199964.22444.043469996.74537.4056210050.9446.88273
10235.2341.5341111026.5540.7068711362.5944.8589411387.0348.6348111421.1145.47965
11562.29 48.556911844.6443.9098812029.25 52.738612061.8350.1549712105.2740.70077
12170.4236.8679512279.0239.6303112344.1852.5591512376.7654.0465912398.4753.66851
12441.9143.0365112485.3545.5137112550.5142.5297812615.6744.1687212637.3848.16668
12680.8243.4996112898.01 47.502213647.3349.8643114059.9946.58779 14243.4 50.9272
#Mann= 3 , 0 , 0
8691.275    0.04       08691.275    0.04       0 14243.4    0.04       0
#XS Ineff= 2 , 0
       09961.732         10481.9       0
Bank Sta=8691.275,14243.4
Exp/Cntr=0.3,0.1

Type RM Length L Ch R = 1 ,10314.52,119.016400,119.016400,119.016400
XS GIS Cut Line= 6
727099.417870104710183.956547812726752.190725267709135.590699077
726745.940725297708777.257365763726175.170229435707765.353028461
723408.148137867706540.224205673723334.147541821706507.459645033
#Sta/Elev= 30
8759.96446.565789548.93240.211349974.94443.067159994.94737.0246710014.9539.26048
10024.9545.4696210054.9642.0597310363.0938.9170511017.5138.3193711472.1846.67173
11515.9243.6039911767.4646.7252511876.8243.5666211904.0846.2862411942.44  43.219
12051.8145.0093312076.9849.2544312150.2337.7789112314.2835.7722712390.8327.75363
12467.3928.5165512576.7541.5872812694.49 42.280212743.8935.7842812795.4835.72449
12828.2941.45001 13014.246.75796 13134.542.6373113682.5149.0793914491.5447.45415
#Mann= 3 , 0 , 0
8759.964  0.0522       08759.964  0.0522       014491.54  0.0522       0
#XS Ineff= 2 , 0
       09965.513        10705.94       0
Bank Sta=8759.964,14491.54
Exp/Cntr=0.3,0.1

Type RM Length L Ch R = 3 ,10259.54,,,
BEGIN DESCRIPTION:
END DESCRIPTION:
Bridge Culvert--1,0,-1,-1, 0
Deck Dist Width WeirC Skew NumUp NumDn MinLoCord MaxHiCord MaxSubmerge Is_Ogee
45.258200,28.500000,2.6,0, 23, 23, , , 0.95, 0, 0,0,,
 9915.83 9918.97 9928.97 9938.97 9948.97 9958.97 9968.97 9975.58 9979.78 9979.78
10020.2210020.2210031.3410038.9710048.9710058.9710068.9710078.9710088.9710098.97
10108.9710118.9710119.82
   41.37   41.41   41.52   41.68   42.00   42.28   42.58   42.83   42.84   42.84
   42.96   42.96   43.00   42.70   42.47   42.18   41.84   41.71   41.51   41.43
   41.23   41.22   41.19
 -958.63 -958.59 -958.48 -958.32 -958.00 -957.72 -957.42 -957.17 -957.16   40.34
   40.46 -957.04 -957.00 -957.30 -957.53 -957.82 -958.16 -958.29 -958.49 -958.57
 -958.77 -958.78 -958.81
 9915.83 9918.97 9928.97 9938.97 9948.97 9958.97 9968.97 9975.58 9979.78 9979.78
10020.2210020.2210031.3410038.9710048.9710058.9710068.9710078.9710088.9710098.97
10108.9710118.9710119.82
   41.37   41.41   41.52   41.68   42.00   42.28   42.58   42.83   42.84   42.84
   42.96   42.96   43.00   42.70   42.47   42.18   41.84   41.71   41.51   41.43
   41.23   41.22   41.19
 -958.63 -958.59 -958.48 -958.32 -958.00 -957.72 -957.42 -957.17 -957.16   40.34
   40.46 -957.04 -957.00 -957.30 -957.53 -957.82 -958.16 -958.29 -958.49 -958.57
 -958.77 -958.78 -958.81
BR Coef=-1 , 0 , 0 ,, 0 ,,,0.8,0,1,0,
WSPro=,,,, 1 ,,,, 0 ,,,, 0 ,,,,-1 ,-1 ,-1 , 0 , 0 , 0 , 0 , 0
BC Design=,, 0 ,, 0 ,,,,,,

Type RM Length L Ch R = 1 , 10195.5,203.249700,203.249700,203.249700
XS GIS Cut Line= 6
727205.159281075710176.255331352726874.412947506709139.757365748
726858.956393421708798.920503423726292.257759362 707728.31423448
723477.592582345706401.335316777723351.932055503706342.092437267
#Sta/Elev= 30
 8755.3946.789279690.92138.843269948.24441.137969968.26546.240819988.28636.53997
10008.3135.9024410028.3343.6641410038.3444.1155210168.4739.0452410551.0737.85153
10947.0841.5640610992.3339.2743411150.7442.9393111252.5740.6987211846.1644.90084
12100.4342.5674412166.7743.6060112199.9447.4830812376.8328.8961512653.2223.14633
12885.3829.2196312940.6640.4194312998.2943.7816113393.9442.9005513725.6148.10191
14024.1145.96349 14170.850.0812614311.5644.1701414554.7844.6716914646.6249.10415
#Mann= 3 , 0 , 0
 8755.39  0.0564       0 8755.39  0.0564       014646.62  0.0564       0
#XS Ineff= 2 , 0
       09968.555         10781.3       0
Bank Sta=8755.39,14646.62
Exp/Cntr=0.3,0.1

Type RM Length L Ch R = 1 ,9992.255,91.009800,91.009800,91.009800
XS GIS Cut Line= 6
727338.222847939710142.666469827727071.287947536709030.382365748
727061.565725267708838.715699077726437.183667034707724.862490177
723434.189804524706288.488094568723353.670131683706249.974397346
#Sta/Elev= 30
8775.82444.873659657.84339.054669975.14342.286429995.16936.0343810025.2143.69589
10055.2540.2551110241.9737.3503110723.4536.2603411170.5542.0743312222.3240.50212
12333.1743.6798412355.3448.8897712455.1135.6902212521.6234.3477412546.9727.11488
12676.8122.9372412755.5428.9895912809.8321.8134112848.2422.4895212965.02 37.4532
13098.0443.3419113195.8740.6657513308.6645.4034413589.8543.1049313983.8347.91926
14073.5344.8669114372.8252.0508114483.6744.42847 14683.243.8638314806.6148.92863
#Mann= 3 , 0 , 0
8775.824  0.0737       08775.824  0.0737       014806.61  0.0737       0
#XS Ineff= 2 , 0
       09965.399        10915.34       0
Bank Sta=8775.824,14806.61
Exp/Cntr=0.3,0.1

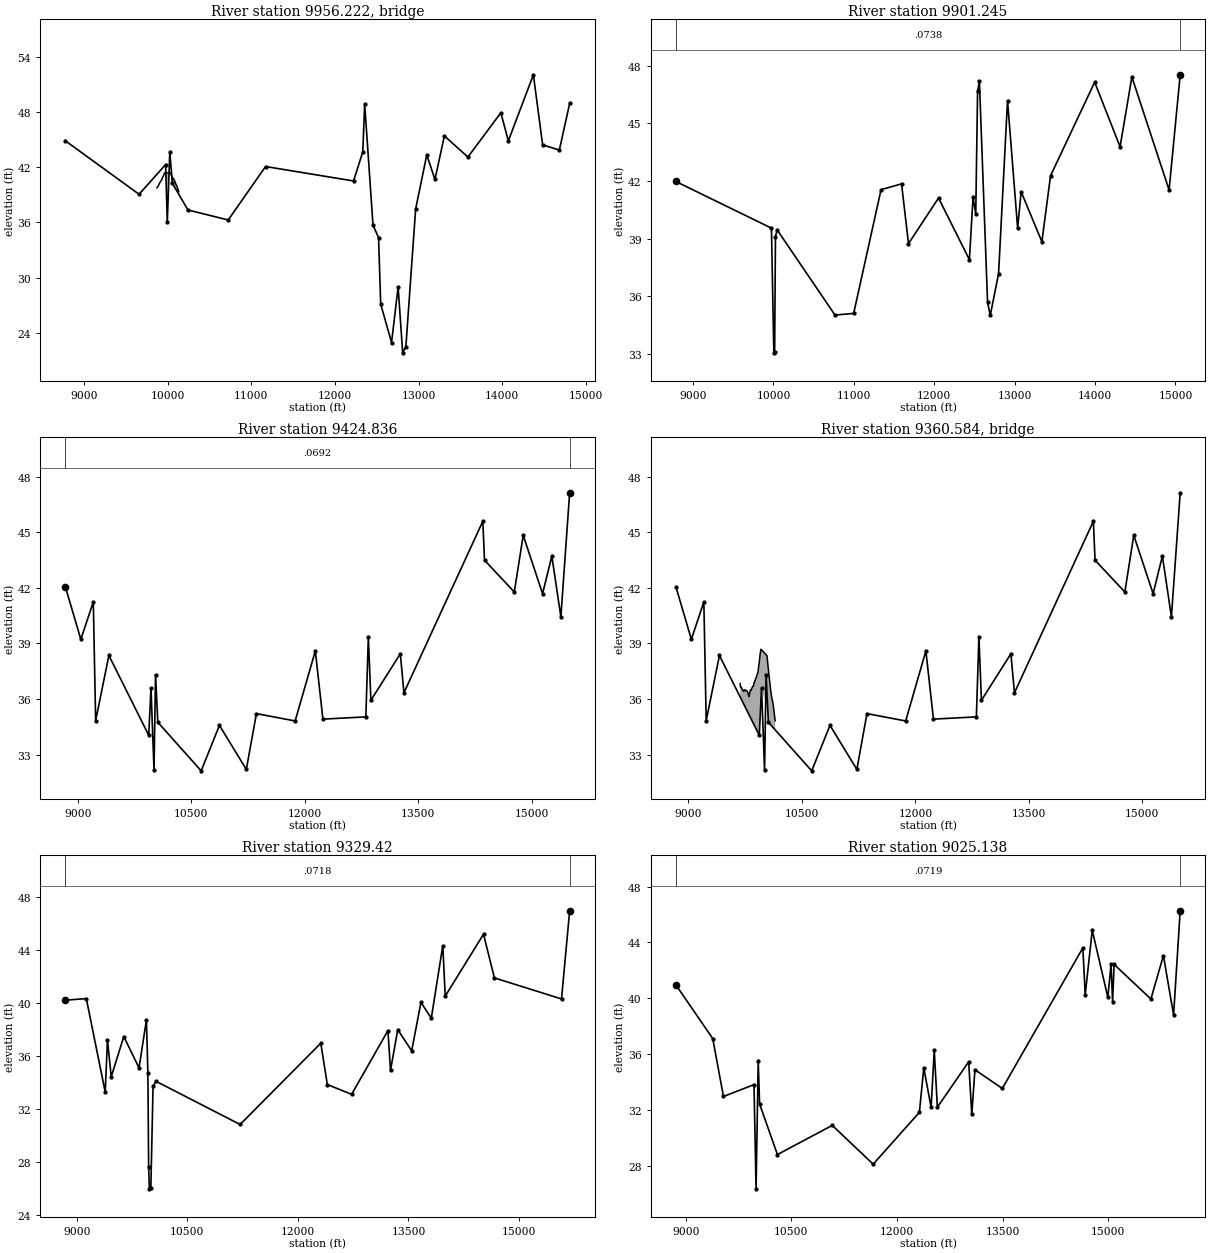
Type RM Length L Ch R = 3 ,9956.222,,,
BEGIN DESCRIPTION:
END DESCRIPTION:
Bridge Culvert--1,0,-1,-1, 0
Deck Dist Width WeirC Skew NumUp NumDn MinLoCord MaxHiCord MaxSubmerge Is_Ogee
31.614900,27.780000,2.6,0, 30, 30, , , 0.95, 0, 0,0,,
 9871.19 9880.66 9890.91 9901.16 9911.41 9913.57 9921.00 9921.65 9931.65 9941.65
 9951.65 9961.65 9962.29 9971.39 9971.3910028.6110028.6110034.3310041.6510051.65
10061.6510071.6510081.6510091.6510101.6510111.6510113.3610122.7410129.7710132.01
   39.76   39.86   40.02   40.25   40.41   40.44   40.52   40.53   40.68   40.95
   41.09   41.37   41.39   41.39   41.39   41.38   41.38   41.38   41.19   40.95
   40.82   40.71   40.54   40.30   40.09   39.92   39.88   39.61   39.39   39.32
 -960.24 -960.14 -959.98 -959.75 -959.59 -959.56 -959.48 -959.47 -959.32 -959.05
 -958.91 -958.63 -958.61 -958.61   38.89   38.88 -958.62 -958.62 -958.81 -959.05
 -959.18 -959.29 -959.46 -959.70 -959.91 -960.08 -960.12 -960.39 -960.61 -960.68
 9871.19 9880.66 9890.91 9901.16 9911.41 9913.57 9921.00 9921.65 9931.65 9941.65
 9951.65 9961.65 9962.29 9971.39 9971.3910028.6110028.6110034.3310041.6510051.65
10061.6510071.6510081.6510091.6510101.6510111.6510113.3610122.7410129.7710132.01
   39.76   39.86   40.02   40.25   40.41   40.44   40.52   40.53   40.68   40.95
   41.09   41.37   41.39   41.39   41.39   41.38   41.38   41.38   41.19   40.95
   40.82   40.71   40.54   40.30   40.09   39.92   39.88   39.61   39.39   39.32
 -960.24 -960.14 -959.98 -959.75 -959.59 -959.56 -959.48 -959.47 -959.32 -959.05
 -958.91 -958.63 -958.61 -958.61   38.89   38.88 -958.62 -958.62 -958.81 -959.05
 -959.18 -959.29 -959.46 -959.70 -959.91 -960.08 -960.12 -960.39 -960.61 -960.68
BR Coef=-1 , 0 , 0 ,, 0 ,,,0.8,0,1,0,
WSPro=,,,, 1 ,,,, 0 ,,,, 0 ,,,,-1 ,-1 ,-1 , 0 , 0 , 0 , 0 , 0
BC Design=,, 0 ,, 0 ,,,,,,

Type RM Length L Ch R = 1 ,9901.245,476.409300,476.409300,476.409300
XS GIS Cut Line= 6
727444.823077977710115.757673889727155.662947506709029.178662032
727160.408317894708813.553662047726641.849422783707709.968453452
723382.106471211 706002.02976121 723352.63296324705986.587149516
#Sta/Elev= 30
8786.23341.976479974.82439.5516610004.83 33.070710014.8333.0938410024.8439.09495
10044.8439.4686310765.5535.0351110997.58 35.119611338.2441.5506511593.3741.85379
11679.5638.7459612053.3341.1185412437.1737.9120312482.3341.15617 12516.240.29881
12538.7846.6529712561.3647.1997912662.9635.6956612696.8335.01986   1280037.18867
12911.3346.1851813037.0239.5553613080.6741.4400813338.6738.8461313446.4142.27504
13995.1247.1371814311.2343.7792814457.9947.4087914920.8641.53299   1505947.52195
#Mann= 3 , 0 , 0
8786.233  0.0738       08786.233  0.0738       0   15059  0.0738       0
#XS Ineff= 2 , 0
       09966.702        11043.09       0
Bank Sta=8786.233,15059
Exp/Cntr=0.3,0.1

Type RM Length L Ch R = 1 ,9424.836,95.416100,95.416100,95.416100
XS GIS Cut Line= 6
727838.868094593710023.702647671727648.960792959709270.377861246
727625.686095685708781.609217614726874.212551713707502.284014747
723390.787026733705802.376983434723353.259298295705784.063501775
#Sta/Elev= 30
8833.651 42.0661 9038.57  39.2259203.57641.242699234.51434.837249409.83338.35453
9936.29134.048389966.32536.5961410006.3732.1583110026.3937.3233210056.4334.75184
10629.4232.1286910871.2434.5822411226.6332.2055211360.0735.21635   1187234.81992
12139.06 38.5998 12239.234.9189712806.6935.0407312840.0739.3692812873.4535.93505
 13262.938.4451813310.3136.3399514353.3745.5941414375.6243.4951414769.6141.77892
14887.4744.83636 15143.441.68643 15265.843.7181415385.2640.44183 15501.447.13287
#Mann= 3 , 0 , 0
8833.651  0.0692       08833.651  0.0692       0 15501.4  0.0692       0
#XS Ineff= 2 , 0
       09961.301        11383.66       0
Bank Sta=8833.651,15501.4
Exp/Cntr=0.3,0.1

Type RM Length L Ch R = 3 ,9360.584,,,
BEGIN DESCRIPTION:
END DESCRIPTION:
Bridge Culvert--1,0,-1,-1, 0
Deck Dist Width WeirC Skew NumUp NumDn MinLoCord MaxHiCord MaxSubmerge Is_Ogee
34.418050,26.580000,2.6,0, 50, 50, , , 0.95, 0, 0,0,,
 9683.94 9688.00 9698.06 9708.11 9714.70 9718.17 9728.23 9738.28 9748.34 9758.39
 9768.45 9778.50 9781.64 9788.52 9798.52 9808.53 9818.53 9828.53 9838.53 9848.53
 9858.53 9868.53 9878.54 9888.54 9898.54 9908.54 9918.54 9928.54 9938.54 9948.55
 9954.08 9958.55 9958.61 9966.69 9966.6910033.3110033.3110038.9110048.5610058.56
10068.5610078.5710088.5710098.5710105.3010108.5910118.6610128.7210138.7910146.66
   36.84   36.65   36.65   36.54   36.51   36.49   36.42   36.51   36.44   36.48
   36.46   36.42   36.39   36.32   36.14   36.29   36.50   36.47   36.59   36.68
   36.70   36.88   36.98   37.09   37.21   37.32   37.45   37.75   38.08   38.46
   38.59   38.69   38.69   38.66   38.66   38.36   38.36   38.34   37.93   37.53
   37.15   36.81   36.43   36.16   36.01   35.95   35.75   35.43   35.09   34.83
 -963.16 -963.35 -963.35 -963.46 -963.49 -963.51 -963.58 -963.49 -963.56 -963.52
 -963.54 -963.58 -963.61 -963.68 -963.86 -963.71 -963.50 -963.53 -963.41 -963.32
 -963.30 -963.12 -963.02 -962.91 -962.79 -962.68 -962.55 -962.25 -961.92 -961.54
 -961.41 -961.31 -961.31 -961.34   36.16   35.86 -961.64 -961.66 -962.07 -962.47
 -962.85 -963.19 -963.57 -963.84 -963.99 -964.05 -964.25 -964.57 -964.91 -965.17
 9683.94 9688.00 9698.06 9708.11 9714.70 9718.17 9728.23 9738.28 9748.34 9758.39
 9768.45 9778.50 9781.64 9788.52 9798.52 9808.53 9818.53 9828.53 9838.53 9848.53
 9858.53 9868.53 9878.54 9888.54 9898.54 9908.54 9918.54 9928.54 9938.54 9948.55
 9954.08 9958.55 9958.61 9966.69 9966.6910033.3110033.3110038.9110048.5610058.56
10068.5610078.5710088.5710098.5710105.3010108.5910118.6610128.7210138.7910146.66
   36.84   36.65   36.65   36.54   36.51   36.49   36.42   36.51   36.44   36.48
   36.46   36.42   36.39   36.32   36.14   36.29   36.50   36.47   36.59   36.68
   36.70   36.88   36.98   37.09   37.21   37.32   37.45   37.75   38.08   38.46
   38.59   38.69   38.69   38.66   38.66   38.36   38.36   38.34   37.93   37.53
   37.15   36.81   36.43   36.16   36.01   35.95   35.75   35.43   35.09   34.83
 -963.16 -963.35 -963.35 -963.46 -963.49 -963.51 -963.58 -963.49 -963.56 -963.52
 -963.54 -963.58 -963.61 -963.68 -963.86 -963.71 -963.50 -963.53 -963.41 -963.32
 -963.30 -963.12 -963.02 -962.91 -962.79 -962.68 -962.55 -962.25 -961.92 -961.54
 -961.41 -961.31 -961.31 -961.34   36.16   35.86 -961.64 -961.66 -962.07 -962.47
 -962.85 -963.19 -963.57 -963.84 -963.99 -964.05 -964.25 -964.57 -964.91 -965.17
BR Coef=-1 , 0 , 0 ,, 0 ,,,0.8,0,1,0,
WSPro=,,,, 1 ,,,, 0 ,,,, 0 ,,,,-1 ,-1 ,-1 , 0 , 0 , 0 , 0 , 0
BC Design=,, 0 ,, 0 ,,,,,,

Type RM Length L Ch R = 1 , 9329.42,304.282200,304.282200,304.282200
XS GIS Cut Line= 6
727936.947881132 710003.20836392727735.408317864709095.498106495
727717.771791995708707.476037383727010.891727269707425.468270093
723425.509249002 705689.52976121723355.532123774705655.648860887
#Sta/Elev= 30
8844.26740.21412 9129.2540.333579385.33833.300699416.06937.212479467.287 34.4441
9637.55937.469579844.65335.113559944.75638.733379964.777 34.70449974.78727.68146
9984.79726.0063410004.8226.0901910034.8533.7175110074.8934.1036211215.9230.85265
12310.7636.9729712399.6533.8588412729.0333.1226613221.8237.9217113256.8234.92517
13355.1537.9945613544.0236.3982813669.8740.0441313810.6738.8625413966.2244.31828
13999.5540.5174314518.9245.1839414666.1841.8911415577.2440.3065915687.7546.94605
#Mann= 3 , 0 , 0
8844.267  0.0718       08844.267  0.0718       015687.75  0.0718       0
#XS Ineff= 2 , 0
       09947.473        11508.92       0
Bank Sta=8844.267,15687.75
Exp/Cntr=0.3,0.1

Type RM Length L Ch R = 1 ,9025.138,88.121000,88.121000,88.121000
XS GIS Cut Line= 6
728180.654504776709952.284591824728027.422206789709006.261995345
728022.213873476708573.970328718727284.016474932707367.532548487
723408.148137867705489.876983434 723360.46869117705466.778784364
#Sta/Elev= 30
 8859.0440.956229383.06637.107259535.02132.956079968.66533.805599998.66726.33752
10028.6735.5260110048.6732.4145910301.8628.7953811080.8730.88504 11662.228.10389
12318.5731.8215512380.9335.0073712485.2532.17589 12529.736.2552512574.1432.18655
13018.6135.4406813063.0631.67463 13107.534.8746413496.4133.5299414640.9143.60811
14674.2540.2480814774.2544.8642914995.7240.0714715041.5942.4329615063.1539.76247
15085.38 42.421115607.6339.9424915785.4143.0571615929.8638.7998816023.79 46.2659
#Mann= 3 , 0 , 0
 8859.04  0.0719       0 8859.04  0.0719       016023.79  0.0719       0
#XS Ineff= 2 , 0
       09942.758        11762.85       0
Bank Sta=8859.04,16023.79
Exp/Cntr=0.3,0.1

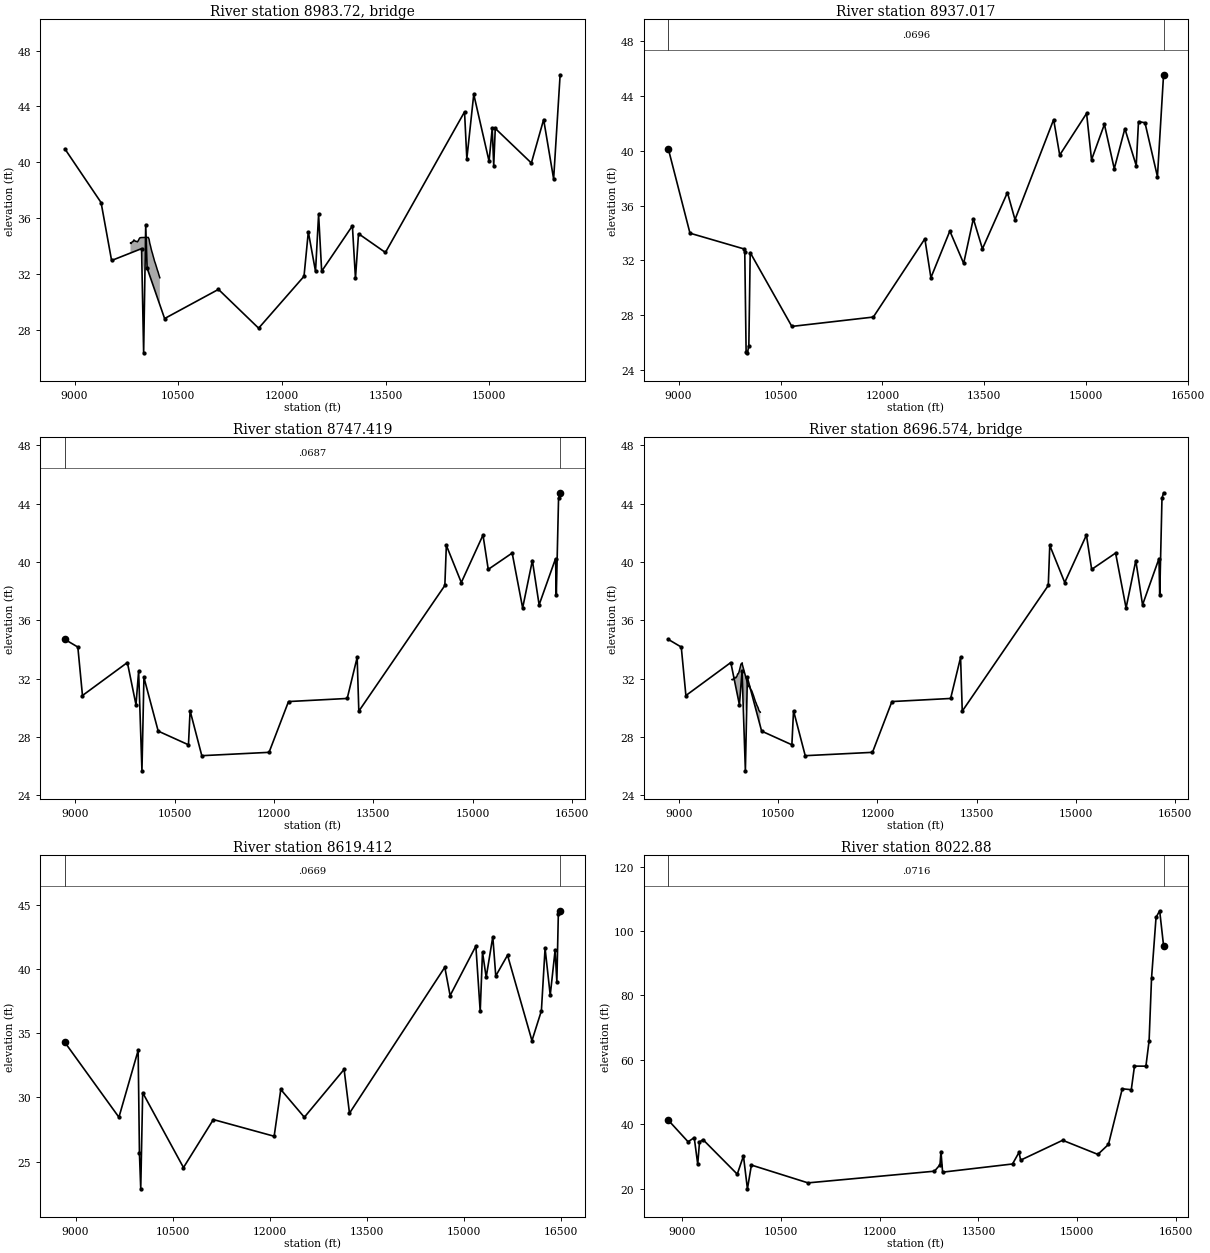
Type RM Length L Ch R = 3 , 8983.72,,,
BEGIN DESCRIPTION:
END DESCRIPTION:
Bridge Culvert--1,0,-1,-1, 0
Deck Dist Width WeirC Skew NumUp NumDn MinLoCord MaxHiCord MaxSubmerge Is_Ogee
30.485500,27.150000,2.6,0, 39, 39, , , 0.95, 0, 0,0,,
 9808.56 9817.44 9827.44 9837.44 9847.44 9857.44 9867.44 9877.44 9887.44 9897.44
 9907.44 9917.44 9927.44 9937.44 9947.44 9953.55 9965.52 9965.5210034.4810034.48
10065.7710067.4410077.4410087.4410097.4410107.4410117.4410127.4410137.4410147.44
10157.4410167.4410177.4410187.4410197.4410207.4410217.4410227.4410233.06
   34.21   34.17   34.26   34.31   34.31   34.43   34.39   34.33   34.33   34.32
   34.29   34.35   34.44   34.54   34.59   34.59   34.60   34.60   34.61   34.61
   34.61   34.59   34.48   34.19   34.01   33.79   33.60   33.44   33.25   33.08
   32.89   32.76   32.60   32.44   32.27   32.14   31.96   31.80   31.72
 -965.79 -965.83 -965.74 -965.69 -965.69 -965.57 -965.61 -965.67 -965.67 -965.68
 -965.71 -965.65 -965.56 -965.46 -965.41 -965.41 -965.40   32.10   32.11 -965.39
 -965.39 -965.41 -965.52 -965.81 -965.99 -966.21 -966.40 -966.56 -966.75 -966.92
 -967.11 -967.24 -967.40 -967.56 -967.73 -967.86 -968.04 -968.20 -968.28
 9808.56 9817.44 9827.44 9837.44 9847.44 9857.44 9867.44 9877.44 9887.44 9897.44
 9907.44 9917.44 9927.44 9937.44 9947.44 9953.55 9965.52 9965.5210034.4810034.48
10065.7710067.4410077.4410087.4410097.4410107.4410117.4410127.4410137.4410147.44
10157.4410167.4410177.4410187.4410197.4410207.4410217.4410227.4410233.06
   34.21   34.17   34.26   34.31   34.31   34.43   34.39   34.33   34.33   34.32
   34.29   34.35   34.44   34.54   34.59   34.59   34.60   34.60   34.61   34.61
   34.61   34.59   34.48   34.19   34.01   33.79   33.60   33.44   33.25   33.08
   32.89   32.76   32.60   32.44   32.27   32.14   31.96   31.80   31.72
 -965.79 -965.83 -965.74 -965.69 -965.69 -965.57 -965.61 -965.67 -965.67 -965.68
 -965.71 -965.65 -965.56 -965.46 -965.41 -965.41 -965.40   32.10   32.11 -965.39
 -965.39 -965.41 -965.52 -965.81 -965.99 -966.21 -966.40 -966.56 -966.75 -966.92
 -967.11 -967.24 -967.40 -967.56 -967.73 -967.86 -968.04 -968.20 -968.28
BR Coef=-1 , 0 , 0 ,, 0 ,,,0.8,0,1,0,
WSPro=,,,, 1 ,,,, 0 ,,,, 0 ,,,,-1 ,-1 ,-1 , 0 , 0 , 0 , 0 , 0
BC Design=,, 0 ,, 0 ,,,,,,

Type RM Length L Ch R = 1 ,8937.017,189.597800,189.597800,189.597800
XS GIS Cut Line= 6
728343.636444151709918.228664175728273.327347517709557.476037383
728103.463873476708996.886995375728117.352762341 708561.12310648
727372.567136317707340.418531239723364.366994798 705364.12345624
#Sta/Elev= 30
8848.67240.153869167.79433.982059963.94132.828839973.94632.620349993.95625.27734
10013.9725.2349110033.98 25.763910053.9932.5618210666.8527.1666111865.9127.85093
12624.0733.5691712713.2730.7291612992.0134.1394213195.2331.7752513337.6435.03824
13471.4432.8389713839.37 36.951413950.8634.9745814519.49  42.28614608.6839.69114
15004.2542.7387815076.9639.34781 15266.5 41.939615411.4538.6933315567.5441.62142
15734.7838.9222815768.2342.1380115863.5342.0566116046.9738.1192216136.8745.56209
#Mann= 3 , 0 , 0
8848.672  0.0696       08848.672  0.0696       016136.87  0.0696       0
#XS Ineff= 2 , 0
       0 9935.71        11827.66       0
Bank Sta=8848.672,16136.87
Exp/Cntr=0.3,0.1

Type RM Length L Ch R = 1 ,8747.419,128.006600,128.006600,128.006600
XS GIS Cut Line= 6
728748.511192858709763.211552054728291.658317864 708998.62310648
728282.977762371708507.303662047728038.186095715708177.442550942
727480.492006332 707303.37085253 723363.97378239705137.225972727
#Sta/Elev= 30
8842.08934.69889 9038.0434.173429107.93530.84904  9786.433.11242 9916.4230.21537
9956.426  32.51810006.43 25.682710036.44 32.087610251.9428.40788   1070927.46935
10733.8129.8044610910.6626.7222411926.5726.9516612220.3730.4350613107.0530.64759
13257.3733.4620913282.5729.7766114582.0738.3973314604.6741.1477614830.6738.59983
15158.3741.8555515237.4739.5008515599.0740.6221815757.26 36.855415904.1640.11011
16006.0937.0694916254.46 40.240916265.7637.7445616299.6644.3701916323.4244.75587
#Mann= 3 , 0 , 0
8842.089  0.0687       08842.089  0.0687       016323.42  0.0687       0
#XS Ineff= 2 , 0
       09918.593        11903.21       0
Bank Sta=8842.089,16323.42
Exp/Cntr=0.3,0.1

Type RM Length L Ch R = 3 ,8696.574,,,
BEGIN DESCRIPTION:
END DESCRIPTION:
Bridge Culvert--1,0,-1,-1, 0
Deck Dist Width WeirC Skew NumUp NumDn MinLoCord MaxHiCord MaxSubmerge Is_Ogee
47.253300,33.500000,2.6,0, 43, 43, , , 0.95, 0, 0,0,,
 9803.74 9809.66 9819.66 9829.66 9839.66 9849.67 9859.67 9869.67 9879.67 9889.67
 9899.67 9909.67 9919.67 9929.67 9939.67 9949.67 9959.67 9960.45 9964.70 9964.70
10035.3010035.3010049.0010049.6810059.6810069.6810079.6810089.6810099.6910109.69
10119.6910129.6910139.6910149.6910159.6910169.6910179.6910189.6910199.6910209.69
10219.6910229.7010231.79
   31.94   31.92   31.98   31.94   32.06   32.10   32.05   32.11   32.18   32.33
   32.34   32.46   32.63   32.81   33.00   33.05   33.09   32.98   32.91   32.91
   31.74   31.74   31.51   31.45   31.54   31.50   31.35   31.25   31.20   31.09
   30.96   30.84   30.70   30.56   30.42   30.33   30.19   30.10   30.00   29.84
   29.77   29.73   29.70
 -968.06 -968.08 -968.02 -968.06 -967.94 -967.90 -967.95 -967.89 -967.82 -967.67
 -967.66 -967.54 -967.37 -967.19 -967.00 -966.95 -966.91 -967.02 -967.09   30.41
   29.24 -968.26 -968.49 -968.55 -968.46 -968.50 -968.65 -968.75 -968.80 -968.91
 -969.04 -969.16 -969.30 -969.44 -969.58 -969.67 -969.81 -969.90 -970.00 -970.16
 -970.23 -970.27 -970.30
 9803.74 9809.66 9819.66 9829.66 9839.66 9849.67 9859.67 9869.67 9879.67 9889.67
 9899.67 9909.67 9919.67 9929.67 9939.67 9949.67 9959.67 9960.45 9964.70 9964.70
10035.3010035.3010049.0010049.6810059.6810069.6810079.6810089.6810099.6910109.69
10119.6910129.6910139.6910149.6910159.6910169.6910179.6910189.6910199.6910209.69
10219.6910229.7010231.79
   31.94   31.92   31.98   31.94   32.06   32.10   32.05   32.11   32.18   32.33
   32.34   32.46   32.63   32.81   33.00   33.05   33.09   32.98   32.91   32.91
   31.74   31.74   31.51   31.45   31.54   31.50   31.35   31.25   31.20   31.09
   30.96   30.84   30.70   30.56   30.42   30.33   30.19   30.10   30.00   29.84
   29.77   29.73   29.70
 -968.06 -968.08 -968.02 -968.06 -967.94 -967.90 -967.95 -967.89 -967.82 -967.67
 -967.66 -967.54 -967.37 -967.19 -967.00 -966.95 -966.91 -967.02 -967.09   30.41
   29.24 -968.26 -968.49 -968.55 -968.46 -968.50 -968.65 -968.75 -968.80 -968.91
 -969.04 -969.16 -969.30 -969.44 -969.58 -969.67 -969.81 -969.90 -970.00 -970.16
 -970.23 -970.27 -970.30
BR Coef=-1 , 0 , 0 ,, 0 ,,,0.8,0,1,0,
WSPro=,,,, 1 ,,,, 0 ,,,, 0 ,,,,-1 ,-1 ,-1 , 0 , 0 , 0 , 0 , 0
BC Design=,, 0 ,, 0 ,,,,,,

Type RM Length L Ch R = 1 ,8619.412,596.532600,596.532600,596.532600
XS GIS Cut Line= 6
  728969.5784536709673.055630058728410.408317894708912.859217599
728406.373262912708429.675505757727770.956596255707575.508839086
727569.970256895707263.834370866723360.587890714704988.144783184
#Sta/Elev= 30
8835.076 34.27739669.76628.448339966.64233.651399986.64325.6446110006.6422.87436
10036.6430.3627210666.6424.5307711127.7928.2690512066.8526.9692512169.1630.61247
12532.9328.4492913146.7932.1758713229.9728.7643514701.8740.1314414783.7637.92394
15181.6341.7820215248.5836.6853715283.9441.3116215340.7839.3485515443.0942.51002
15488.5639.4527615670.4541.0675116047.6234.4111416193.3736.7416916250.21 41.6073
16329.7837.9538916405.0841.4502816432.0938.9877416454.8344.2488116482.5844.52715
#Mann= 3 , 0 , 0
8835.076  0.0669       08835.076  0.0669       016482.58  0.0669       0
#XS Ineff= 2 , 0
       0 9918.37        11983.73       0
Bank Sta=8835.076,16482.58
Exp/Cntr=0.3,0.1

Type RM Length L Ch R = 1 , 8022.88,262.984000,262.984000,262.984000
XS GIS Cut Line= 6
729792.363512725 709202.16797927 729306.97583136708760.955765933
728915.963873416708495.498106465728878.463873446708153.831439808
 728295.44038415707453.025427461724137.314804554704448.210316792
#Sta/Elev= 30
8792.69341.23187 9092.9834.518119186.22435.812059239.50727.520419266.148 34.4428
9319.43135.191249839.17124.460779933.17430.114299993.535 19.9042 10053.927.28999
10912.8221.7571412831.7525.3868612916.0527.3786612930.4531.4889412955.1325.08467
14016.1827.6249514114.8831.2342514139.5628.8130114777.03 34.986615311.64  30.603
15472.0333.6986615681.7850.98337 15818.550.6934215866.8458.0182816040.4558.01326
16088.9265.9013516125.8285.3318916194.11104.212716249.31106.268216308.1595.44803
#Mann= 3 , 0 , 0
8792.693  0.0716       08792.693  0.0716       016308.15  0.0716       0
#XS Ineff= 2 , 0
       09905.705        12181.41       0
Bank Sta=8792.693,16308.15
Exp/Cntr=0.3,0.1