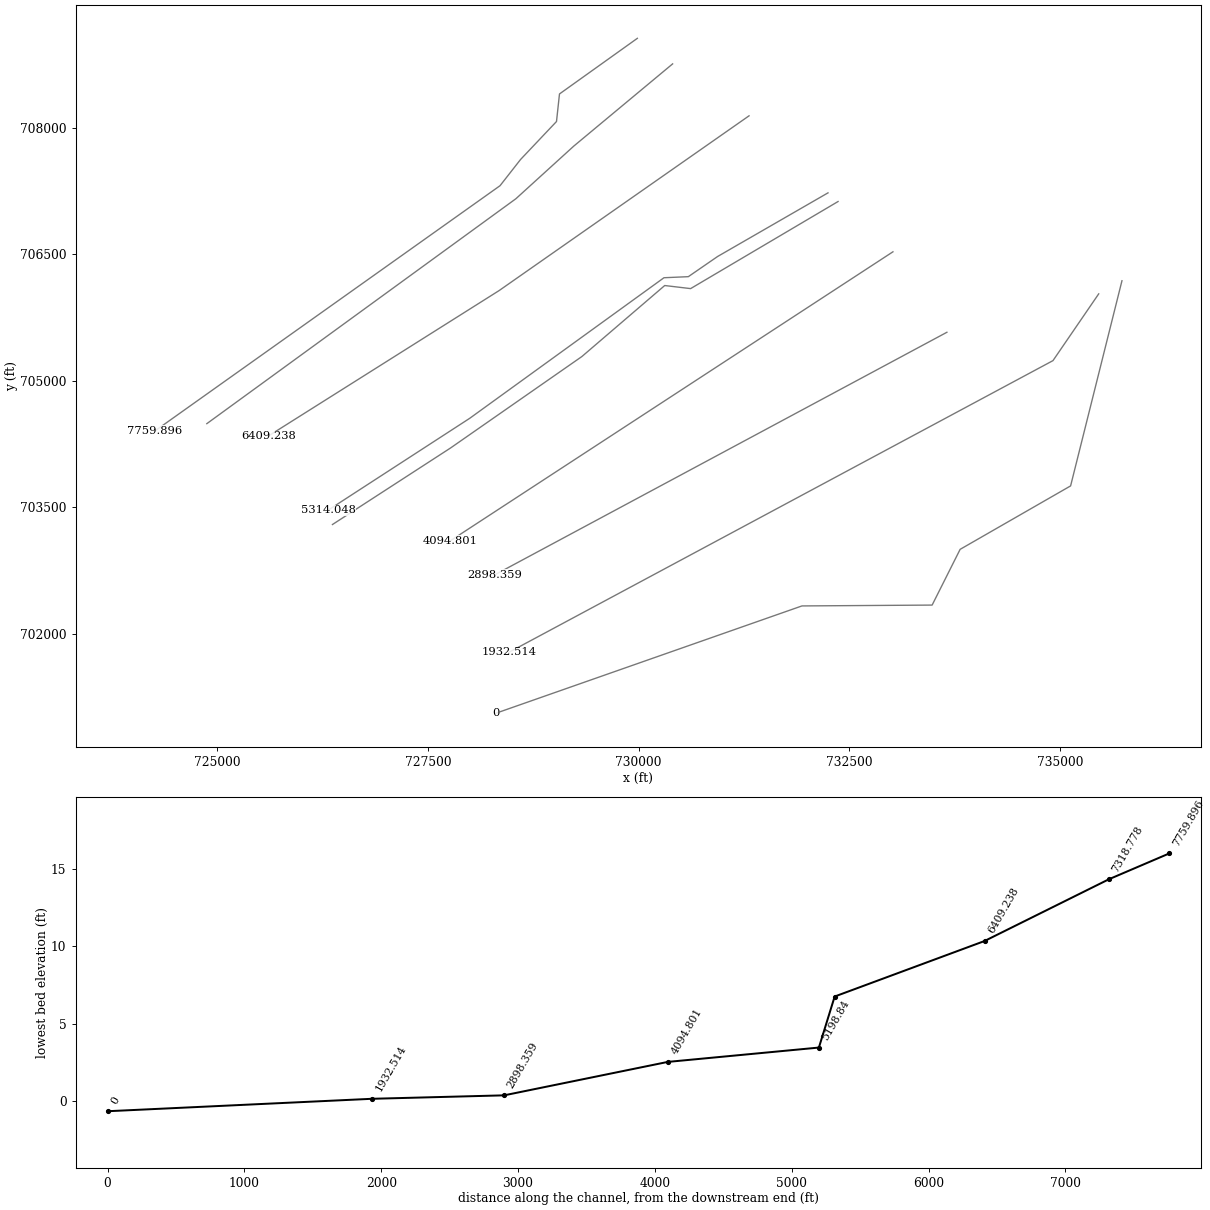
HEC-RAS study 6177_ras.prj: 6177

--- 6177_ras.g01 (geometry) --- (continued)

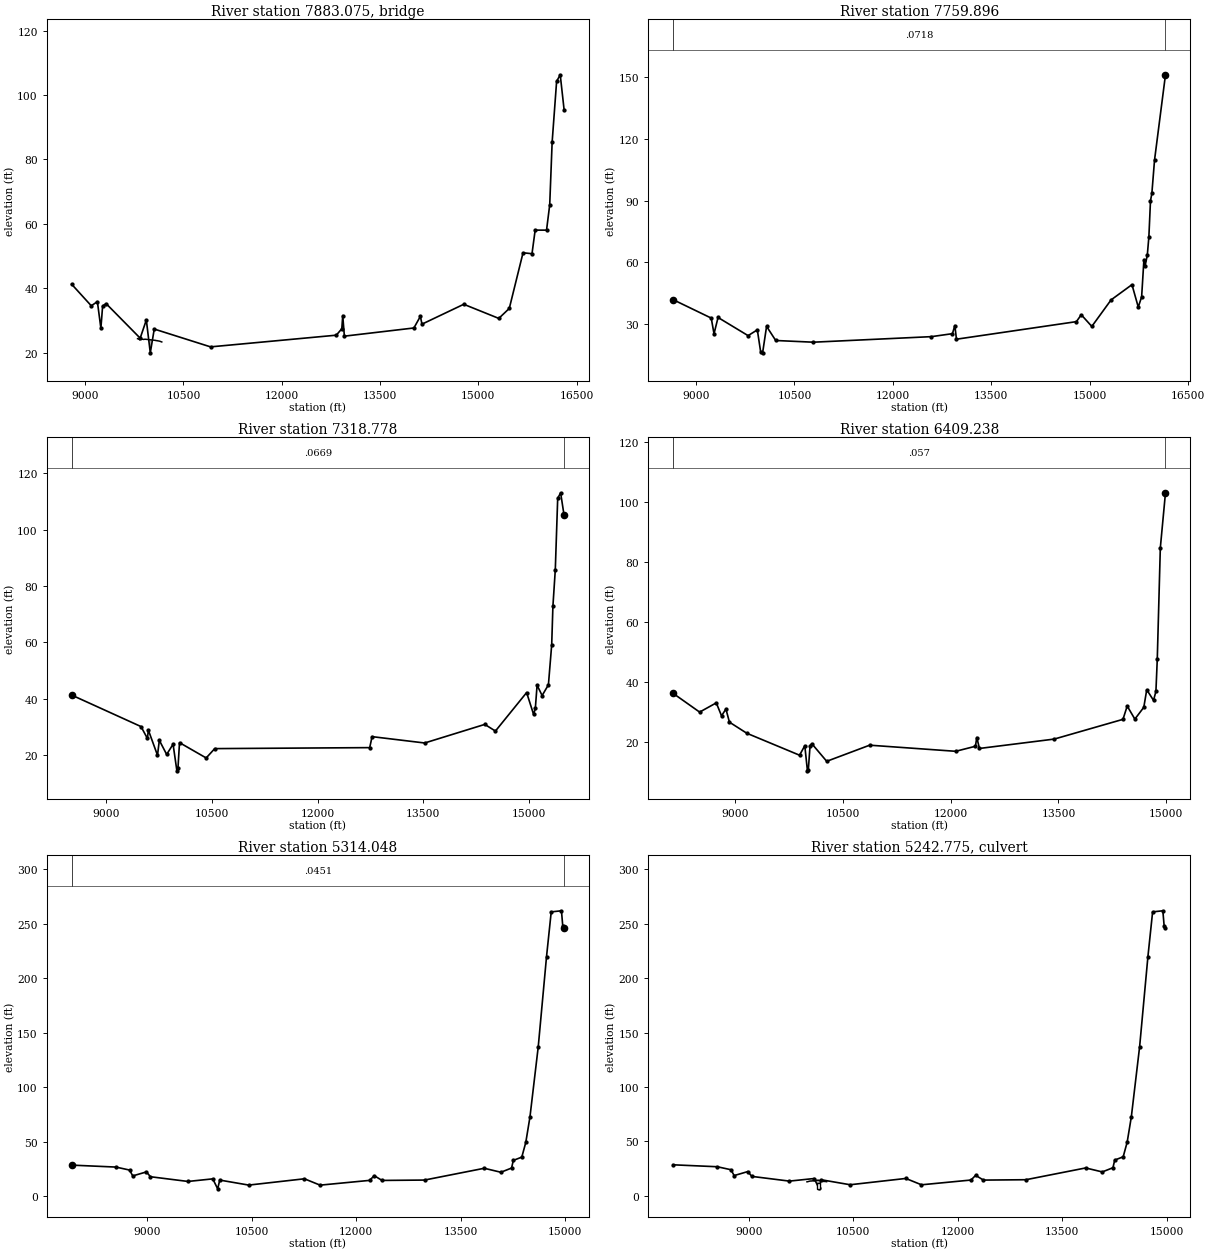
Type RM Length L Ch R = 3 ,7883.075,,,
BEGIN DESCRIPTION:
END DESCRIPTION:
Bridge Culvert--1,0,-1,-1, 0
Deck Dist Width WeirC Skew NumUp NumDn MinLoCord MaxHiCord MaxSubmerge Is_Ogee
114.742000,33.500000,2.6,0, 30, 30, , , 0.95, 0, 0,0,,
 9799.04 9800.45 9810.45 9820.46 9830.46 9840.47 9850.47 9860.48 9870.49 9880.49
 9882.53 9890.50 9900.51 9910.52 9917.76 9945.00 9945.0010055.0010055.0010075.43
10080.7210090.7410100.7510110.7610120.7710130.7810140.7910150.8110160.8210168.38
   24.31   24.30   24.21   24.22   23.95   24.16   24.12   24.13   24.13   24.11
   24.10   24.06   24.10   24.13   24.13   24.07   24.07   23.81   23.81   23.77
   23.69   23.70   23.68   23.60   23.60   23.55   23.48   23.44   23.32   23.29
 -975.69 -975.70 -975.79 -975.78 -976.05 -975.84 -975.88 -975.87 -975.87 -975.89
 -975.90 -975.94 -975.90 -975.87 -975.87 -975.93   21.57   21.31 -976.19 -976.23
 -976.31 -976.30 -976.32 -976.40 -976.40 -976.45 -976.52 -976.56 -976.68 -976.71
 9799.04 9800.45 9810.45 9820.46 9830.46 9840.47 9850.47 9860.48 9870.49 9880.49
 9882.53 9890.50 9900.51 9910.52 9917.76 9945.00 9945.0010055.0010055.0010075.43
10080.7210090.7410100.7510110.7610120.7710130.7810140.7910150.8110160.8210168.38
   24.31   24.30   24.21   24.22   23.95   24.16   24.12   24.13   24.13   24.11
   24.10   24.06   24.10   24.13   24.13   24.07   24.07   23.81   23.81   23.77
   23.69   23.70   23.68   23.60   23.60   23.55   23.48   23.44   23.32   23.29
 -975.69 -975.70 -975.79 -975.78 -976.05 -975.84 -975.88 -975.87 -975.87 -975.89
 -975.90 -975.94 -975.90 -975.87 -975.87 -975.93   21.57   21.31 -976.19 -976.23
 -976.31 -976.30 -976.32 -976.40 -976.40 -976.45 -976.52 -976.56 -976.68 -976.71
BR Coef=-1 , 0 , 0 ,, 0 ,,,0.8,0,1,0,
WSPro=,,,, 1 ,,,, 0 ,,,, 0 ,,,,-1 ,-1 ,-1 , 0 , 0 , 0 , 0 , 0
BC Design=,, 0 ,, 0 ,,,,,,

Type RM Length L Ch R = 1 ,7759.896,441.117400,441.117400,441.117400
XS GIS Cut Line= 6
729983.574039161709063.731558129729059.713873446708403.831439838
729024.297206789 708076.74810648728597.806245267707626.116147116
728354.289929539707315.092172414724258.842582345704404.807539001
#Sta/Elev= 30
 8649.4541.876669232.22532.890619274.43825.276129335.88333.190359793.66824.36303
9934.48627.173699984.77816.5112410014.9515.99923 10075.328.8617210214.5922.00044
10787.4521.1744612588.2423.87589 12907.225.31777   1294429.2678412968.5422.62646
14796.4331.1718614870.0434.5228915030.9728.8432615324.4541.73936 15642.949.14971
15738.7838.2386615790.1243.2161715825.09 61.344815842.3658.1468315876.8963.60237
15900.53 72.490215925.0689.9234815945.9493.47291 15986.4109.650616153.43151.1908
#Mann= 3 , 0 , 0
 8649.45  0.0718       0 8649.45  0.0718       016153.43  0.0718       0
#XS Ineff= 2 , 0
       09889.883        12108.97       0
Bank Sta=8649.45,16153.43
Exp/Cntr=0.3,0.1

Type RM Length L Ch R = 1 ,7318.778,909.540100,909.540100,909.540100
XS GIS Cut Line= 4
730402.190438211708760.653285205729229.559858412707785.190678999
728542.059858412707160.190678999724875.162026733704491.613094568
#Sta/Elev= 30
8509.21441.238259494.14130.048139585.19425.820969598.20228.812049728.27919.87042
9754.29425.159239858.35520.153679949.40923.7780610003.5614.3313110019.1915.45719
10040.6924.34416 10419.118.9044810540.7322.2212112739.9222.5710712773.9126.47019
13520.1524.2187314373.5330.8204714524.3528.4475714967.1842.1210315066.1234.35042
15090.8636.5353915115.5944.7411215187.1441.0655315276.3844.8686315323.0959.12812
15340.0972.7099515374.0885.7277815408.07 111.04915449.52113.048615498.79105.0378
#Mann= 3 , 0 , 0
8509.214  0.0669       08509.214  0.0669       015498.79  0.0669       0
#XS Ineff= 2 , 0
       09916.747        12021.42       0
Bank Sta=8509.214,15498.79
Exp/Cntr=0.3,0.1

Type RM Length L Ch R = 1 ,6409.238,1095.190000,1095.190000,1095.190000
XS GIS Cut Line= 3
731308.890768945708144.266929299728342.889136761706070.382975578
 725604.32869342704344.043650106
#Sta/Elev= 30
 8132.9936.22476  8503.829.94296 8735.6433.022828808.85228.695358869.86330.96609
8918.67126.584349161.32122.875929894.837 15.5578 9968.0518.7360410004.6610.33902
10016.8610.5806310041.2618.7498210065.6719.39961 10273.113.51697   1087118.90032
 12068.816.8598312343.5418.54227 12362.321.46129 12399.817.8101713440.0520.93533
14397.5627.5258514456.6631.9545814563.0527.6006214687.5831.5399214728.5537.40496
14823.1233.8555714856.3536.85668 14875.147.5454214917.6984.7722714989.41103.1354
#Mann= 3 , 0 , 0
 8132.99   0.057       0 8132.99   0.057       014989.41   0.057       0
#XS Ineff= 2 , 0
       09940.765        12078.96       0
Bank Sta=8132.99,14989.41
Exp/Cntr=0.3,0.1

Type RM Length L Ch R = 1 ,5314.048,115.208500,115.208500,115.208500
XS GIS Cut Line= 6
 732245.82498455707230.220328702730935.641611247706474.909391414
730588.460733564706235.763650954730299.586860656706223.070885031
727994.068864731704554.733376097726313.513309213703464.455598314
#Sta/Elev= 30
7911.63228.506988547.43326.72409 8743.6623.98476 8789.8318.618498986.05722.28012
 9043.7717.862159582.57513.53149 9939.0915.9047410009.186.75375210039.2114.79042
10455.3210.1938311255.0915.9706911480.0510.1375612191.0614.5148512257.6418.82855
12369.6714.4635912979.6114.80493 13837.925.6199914076.3121.9650314229.6925.81923
14255.1132.8441714376.6835.8588214433.9149.3043114493.5172.4944114612.71136.9721
14731.91219.782514799.27260.787614946.26 261.80214964.63248.068914984.01245.9012
#Mann= 3 , 0 , 0
7911.632  0.0451       07911.632  0.0451       014984.01  0.0451       0
#XS Ineff= 2 , 0
       09928.708        11923.71       0
Bank Sta=7911.632,14984.01
Exp/Cntr=0.3,0.1

Type RM Length L Ch R = 2 ,5242.775,,,
Bridge Culvert--1,0,-1,-1, 0
Deck Dist Width WeirC Skew NumUp NumDn MinLoCord MaxHiCord MaxSubmerge Is_Ogee
33.604,48,2.6,0,34,34, , , 0.95, 0, 0,0,,
 9835.71 9837.51 9844.62 9847.85 9858.18 9868.51 9878.84 9880.59 9888.93 9898.97
 9909.01 9919.05 9929.09 9939.14 9949.18 9959.22 9969.26 9979.30 9979.61 9989.35
 9999.3910009.4310019.4710029.5110039.5510049.6010059.6410069.6810079.7210089.33
10089.7610099.8110109.8510117.93
   12.88   12.89   12.94   13.00   13.22   13.43   13.56   13.59   13.62   13.62
   13.73   13.75   13.85   14.03   14.01   14.02   14.19   14.31   14.31   14.35
   14.34   14.25   14.02   13.80   13.59   13.34   13.28   13.28   13.20   13.24
   13.24   13.13   13.14   12.99
                                                                                
                                                                                
                                                                                
                                
 9835.71 9837.51 9844.62 9847.85 9858.18 9868.51 9878.84 9880.59 9888.93 9898.97
 9909.01 9919.05 9929.09 9939.14 9949.18 9959.22 9969.26 9979.30 9979.61 9989.35
 9999.3910009.4310019.4710029.5110039.5510049.6010059.6410069.6810079.7210089.33
10089.7610099.8110109.8510117.93
   12.88   12.89   12.94   13.00   13.22   13.43   13.56   13.59   13.62   13.62
   13.73   13.75   13.85   14.03   14.01   14.02   14.19   14.31   14.31   14.35
   14.34   14.25   14.02   13.80   13.59   13.34   13.28   13.28   13.20   13.24
   13.24   13.13   13.14   12.99
                                                                                
                                                                                
                                                                                
                                
BR Coef=-1 , 0 , 0 ,, 0 ,,,0.8,-1,,0,
WSPro=,,,, 1 ,,,, 0 ,,,, 0 ,,,,-1 ,-1 ,-1 , 0 , 0 , 0 , 0 , 0
Culvert=2,5,32,48,0.013,0.4,1,8,1,6.43,10000,3.32,10000,Culvert #1, 0, 33.604
Culvert Bottom n=0.013
BC Design=,, 0 ,, 0 ,,,,,,

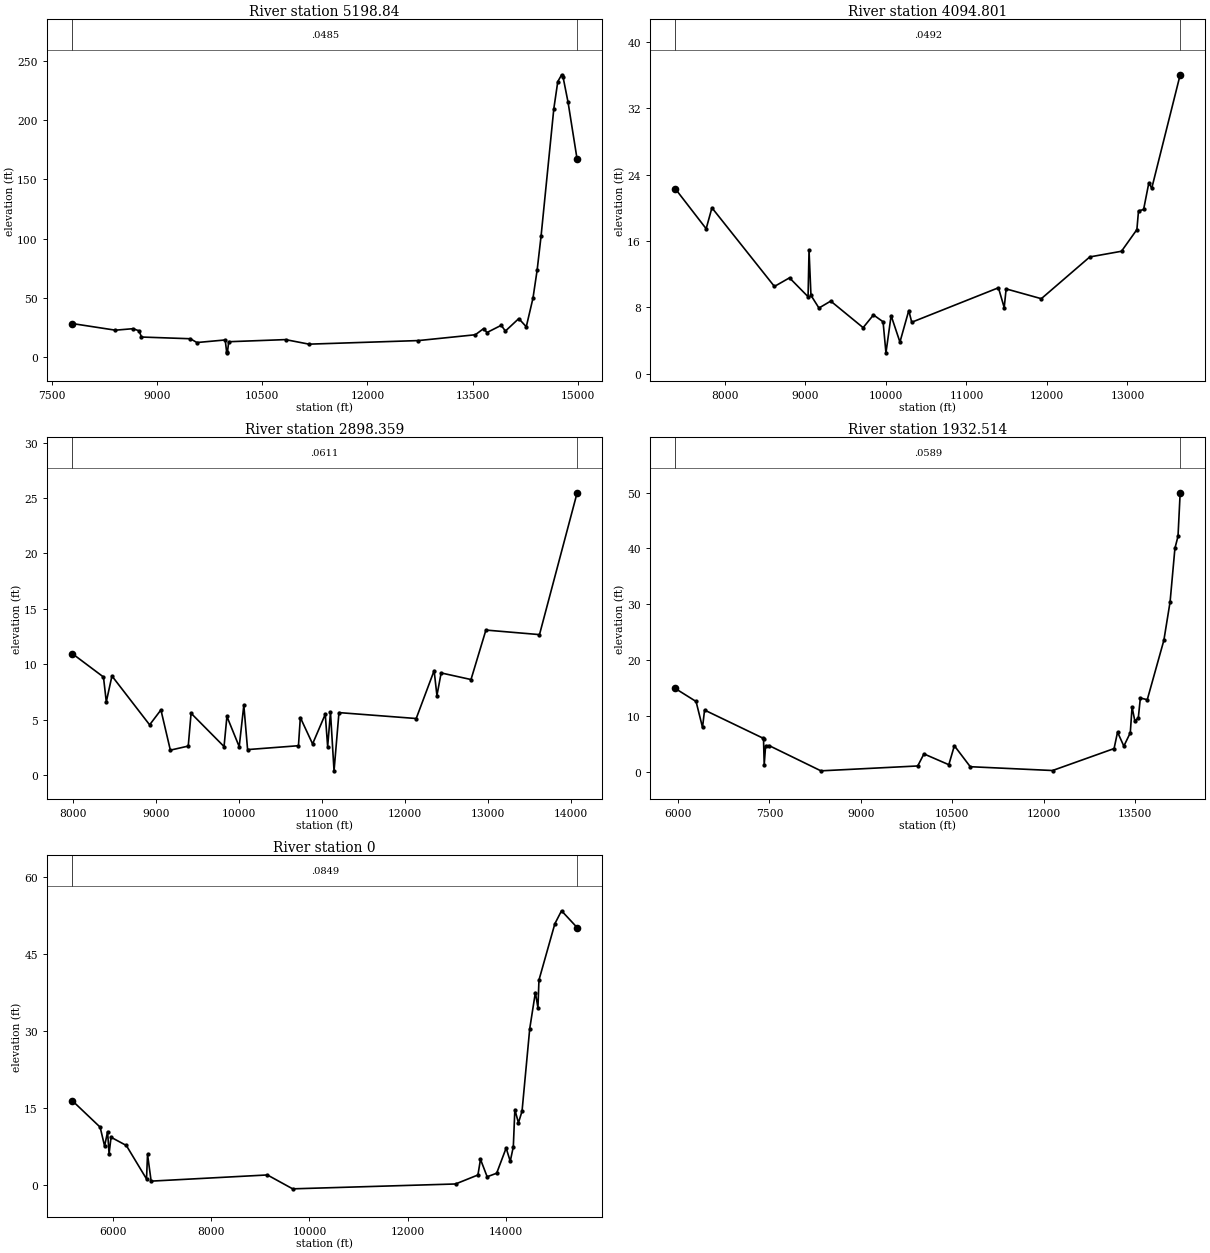
Type RM Length L Ch R = 1 , 5198.84,1104.038700,1104.038700,1104.038700
XS GIS Cut Line= 6
732365.269429028707127.442550927730615.616651207706094.109217614
 730308.32498455706130.567550912729325.686095655705288.206439823
 727767.48303017704203.200010777726365.813960284703294.807292625
#Sta/Elev= 30
7787.01728.199148403.55622.591918654.265 23.85858740.73622.057168775.61716.80872
9473.23115.360599566.24612.155979970.42814.336579990.6194.31989710000.713.456995
 10020.9 12.845710830.8914.6357211166.7110.7873412728.8413.8238813540.2418.73333
13659.5223.9845513705.72 20.600413909.7626.7073913969.3421.8472614160.0132.38014
14267.2525.4887914362.5849.5611414422.1773.2731814477.99101.832314660.49209.7399
14717.02232.602914772.18238.329114791.58236.609414864.12214.962114993.18166.8038
#Mann= 3 , 0 , 0
7787.017  0.0485       07787.017  0.0485       014993.18  0.0485       0
#XS Ineff= 2 , 0
       09902.714        11799.95       0
Bank Sta=7787.017,14993.18
Exp/Cntr=0.3,0.1

Type RM Length L Ch R = 1 ,4094.801,1196.442400,1196.442400,1196.442400
XS GIS Cut Line= 2
733016.497696817706530.847186878727764.761585712703102.027742431
#Sta/Elev= 30
7382.34722.28883  7766.317.471017837.95619.992748614.22810.522688801.51911.56009
9032.2219.2858379044.164 14.87089068.0499.4528379167.3577.9253849313.6928.761095
9716.114 5.563339844.3217.0954939963.748 6.272989999.5752.53073810063.667.012376
10173.413.82716910283.167.62568310319.75 6.2146511396.8710.3644711468.527.977379
11492.4110.2284211929.439.04914912531.4214.0761712925.5214.7603113116.61 17.3667
 13136.719.6141713200.21 19.790713264.7422.9772113301.3322.3491113654.3136.00594
#Mann= 3 , 0 , 0
7382.347  0.0492       07382.347  0.0492       013654.31  0.0492       0
#XS Ineff= 2 , 0
       0                10988.93       0
Bank Sta=7382.347,13654.31
Exp/Cntr=0.3,0.1

Type RM Length L Ch R = 1 ,2898.359,965.844500,965.844500,965.844500
XS GIS Cut Line= 2
733656.688669026705575.986075774728296.445613503702700.552047998
#Sta/Elev= 30
7992.653 10.95428369.0528.8404988403.0966.6012818471.1848.9336038925.103 4.52254
9061.2785.8698639174.7582.237666 9390.372.6058949424.414 5.568269821.5932.561895
 9856.325.278167 10004.4 2.55221 10059.96.29586710105.292.28893510718.082.638211
10740.785.177641 10888.32.80160711040.965.47505211069.872.56282411103.915.649137
11146.730.37054911206.055.62707812136.585.09312812352.539.41537612386.237.170196
12437.15 9.2074612796.77 8.6117912976.3313.0767213621.7912.6667514075.4425.46891
#Mann= 3 , 0 , 0
7992.653  0.0611       07992.653  0.0611       014075.44  0.0611       0
#XS Ineff= 2 , 0
       0                11369.84       0
Bank Sta=7992.653,14075.44
Exp/Cntr=0.3,0.1

Type RM Length L Ch R = 1 ,1932.514,1932.514100,1932.514100,1932.514100
XS GIS Cut Line= 3
735457.903946817706031.715242445734915.369224638705239.614547983
 728459.20603019701778.243020207
#Sta/Elev= 30
5953.44914.902836294.81812.570876400.9967.9187516434.29911.033947388.902  6.0244
7401.8565.8755457413.2031.2198137435.8964.6135357492.6294.6743438343.6190.147495
9932.1351.02116810034.353.17957510442.73 1.24667 10533.54.64476110794.470.887601
12144.710.20472413154.55 4.1364913211.297.07645413314.714.57658113420.536.961297
13449.5611.5748313494.959.09256813551.689.59658313585.7213.1917913699.1912.88849
 13971.523.5273914073.6230.4140614153.0540.0201514203.5942.1551814239.0549.95124
#Mann= 3 , 0 , 0
5953.449  0.0589       05953.449  0.0589       014239.05  0.0589       0
#XS Ineff= 2 , 0
       0                11774.42       0
Bank Sta=5953.449,14239.05
Exp/Cntr=0.3,0.1

Type RM Length L Ch R = 1 ,       0,0.000000,0.000000,0.000000
XS GIS Cut Line= 6
735733.939814387 706187.26724125735124.494515805703753.140625939
733813.661182524703000.362848183733481.449308784702338.873899734
731936.647293597702328.835070373728300.606481014701053.933907919
#Sta/Elev= 30
5178.93316.515395746.17611.350885836.9727.6593355897.50310.483635927.7696.172166
5967.8959.3848276278.4477.7841546688.6361.2680286709.4786.0440896782.4230.844125
9144.6812.047519 9658.57-0.6561712968.530.290605 13423.32.04108613475.42 5.09256
13610.911.692788   138042.38304413996.567.28601314079.944.71036714142.477.530365
14173.7414.76773 14246.712.1962114319.6614.46102   14476  30.51714590.6537.55911
14642.7734.6063514663.61 39.989714986.7250.9533415122.2153.4756515439.4850.20445
#Mann= 3 , 0 , 0
5178.933  0.0849       05178.933  0.0849       015439.48  0.0849       0
#XS Ineff= 2 , 0
       0                13036.91       0
Bank Sta=5178.933,15439.48
Exp/Cntr=0.3,0.1